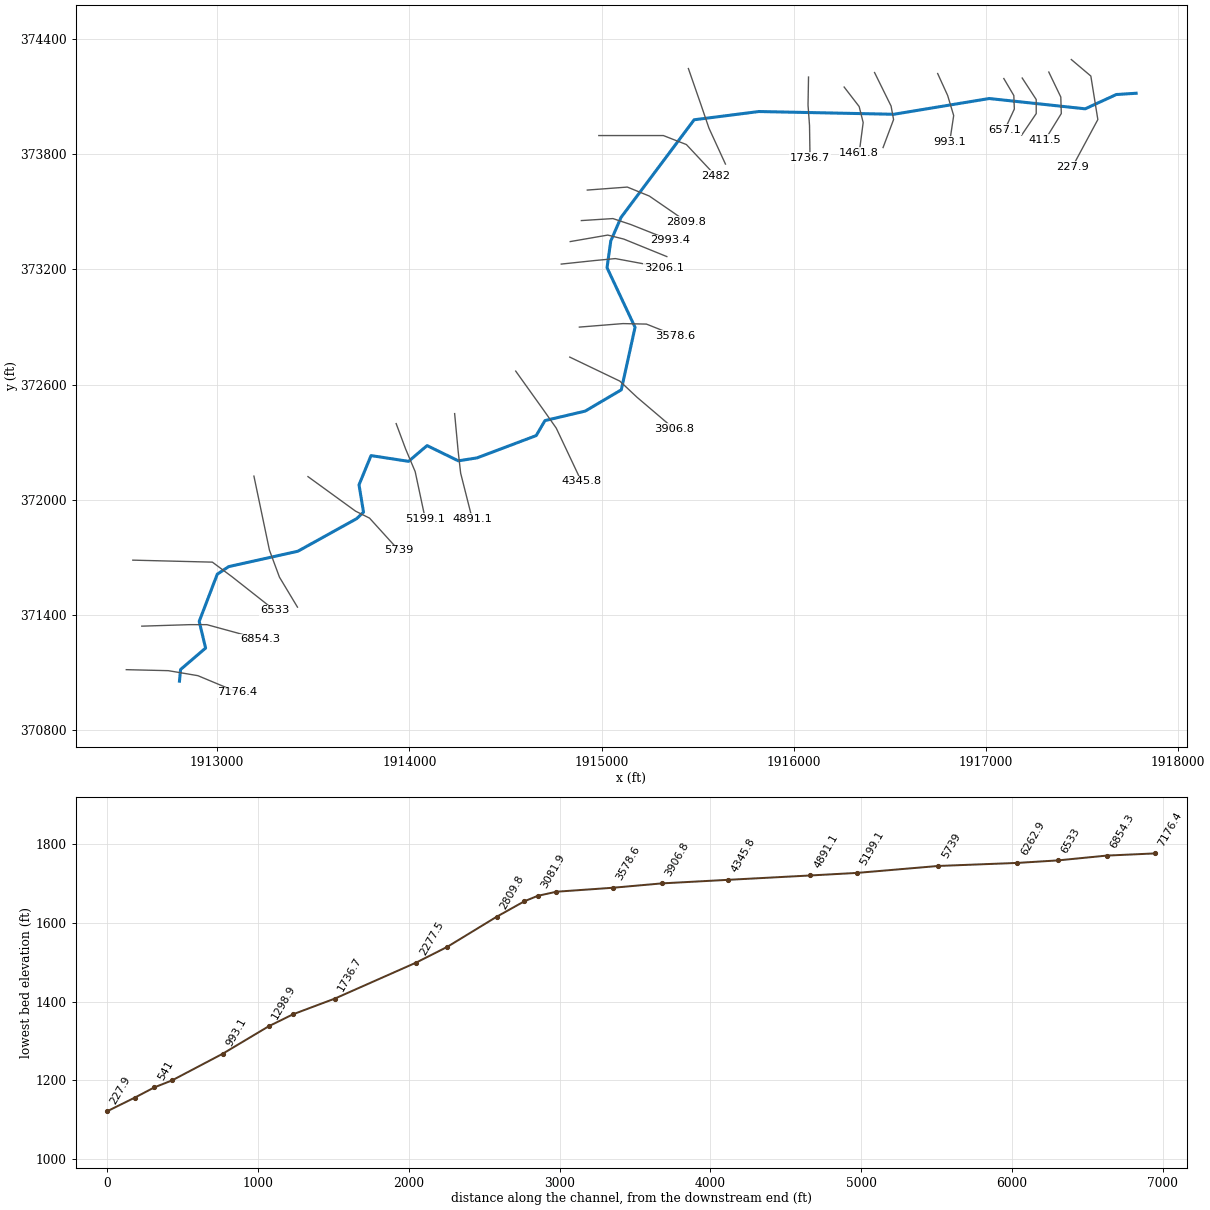
--- LAURELRN1.prj (project) ---

Proj Title=LAURELRN1
Current Plan=p01
Default Exp/Contr=0,0
English Units
Geom File=g01
Flow File=f01
Plan File=p01
BEGIN DESCRIPTION:
END DESCRIPTION:
DSS Export Rating Curves= 0
DSS Export Rating Curve Sorted= 0
DSS Export Volume Flow Curves= 0
DXF OffsetX= 0
DXF OffsetY= 0
DXF ScaleX= 0
DXF ScaleY= 0

--- LAURELRN1.p01 (plan) ---

Plan Title=Floodplain
Program Version=4.00
Geom File=g01
Flow File=f01
K Sum by GR=0
Std Step Tol=0.01
Critical Tol=0.01
Num of Std Step Trials=20
Max Error Tol=0.3
Flow Tol Ratio=0.001
Split Flow NTrial=30
Split Flow Tol=0.02
Split Flow Ratio=0.02
Log Output Level=0
Friction Slope Method=1
Unsteady Friction Slope Method=2
Unsteady Bridges Friction Slope Method=1
Global Log Level=0
CheckData=False
Run HTab=0
Run UNet=0
Run PostProcess=0
UNET Theta=0
UNET Theta Warmup=0
UNET ZTol=0
UNET ZSATol=0
UNET MxIter=0
UNET MaxInSteps=0
UNET DtIC=0
UNET DtMin=0
UNET MaxCRTS=0
UNET WFStab=0
UNET SFStab=0
UNET WFX=0
UNET SFX=0
UNET DSS MLevel=0
UNET DZMax Abort=0
UNET Convert EG Bridges=0
UNET Use Existing IB Tables=0
UNET Froude Limit=0
UNET Froude Power=0
Write IC File=0
Echo Input=False
Echo Output=False
Write Detailed=0

--- LAURELRN1.f01 (steady flow) ---

Flow Title=NFF Regression Equation
Program Version=4.00
Number of Profiles=1
Profile Names=P100yr
River Rch & RM=LAURELRN1,Main      ,7176.4
515.4864
River Rch & RM=LAURELRN1,Main      ,6533
522.5401
River Rch & RM=LAURELRN1,Main      ,6262.9
666.7077
River Rch & RM=LAURELRN1,Main      ,2482
728.5023
River Rch & RM=LAURELRN1,Main      ,2277.5
854.1388
River Rch & RM=LAURELRN1,Main      ,227.9
876.3393
Boundary for River Rch & Prof#=LAURELRN1,Main      ,1
Up Type=0
Dn Type=3
Dn Slope=0.178527

--- LAURELRN1.g01 (geometry) ---

Geom Title=USGS 10m DEM
Program Version=4.10

River Reach=LAURELRN1       ,Main
Reach XY= 30
     1912804.165      371055.092     1912809.978      371115.957
     1912940.119      371227.596     1912906.896      371366.412
      1913000.95      371612.485     1913060.428      371651.867
     1913420.358      371731.957     1913726.536      371901.765
     1913761.693      371935.619     1913738.255      372077.546
     1913800.755       372229.89     1913996.068      372199.942
     1914092.422      372281.973     1914255.182      372202.546
     1914352.838      372218.171      1914660.13      372334.056
     1914705.703      372412.181     1914915.338       372461.66
     1915102.838      372572.338     1915174.453      372897.858
      1915028.62      373208.405     1915048.151      373347.728
     1915101.536      373470.124     1915481.745      373978.588
     1915818.984      374021.556     1916520.807      374007.233
     1917016.901      374089.265      1917516.27      374035.644
     1917678.359      374110.098     1917781.224      374116.608

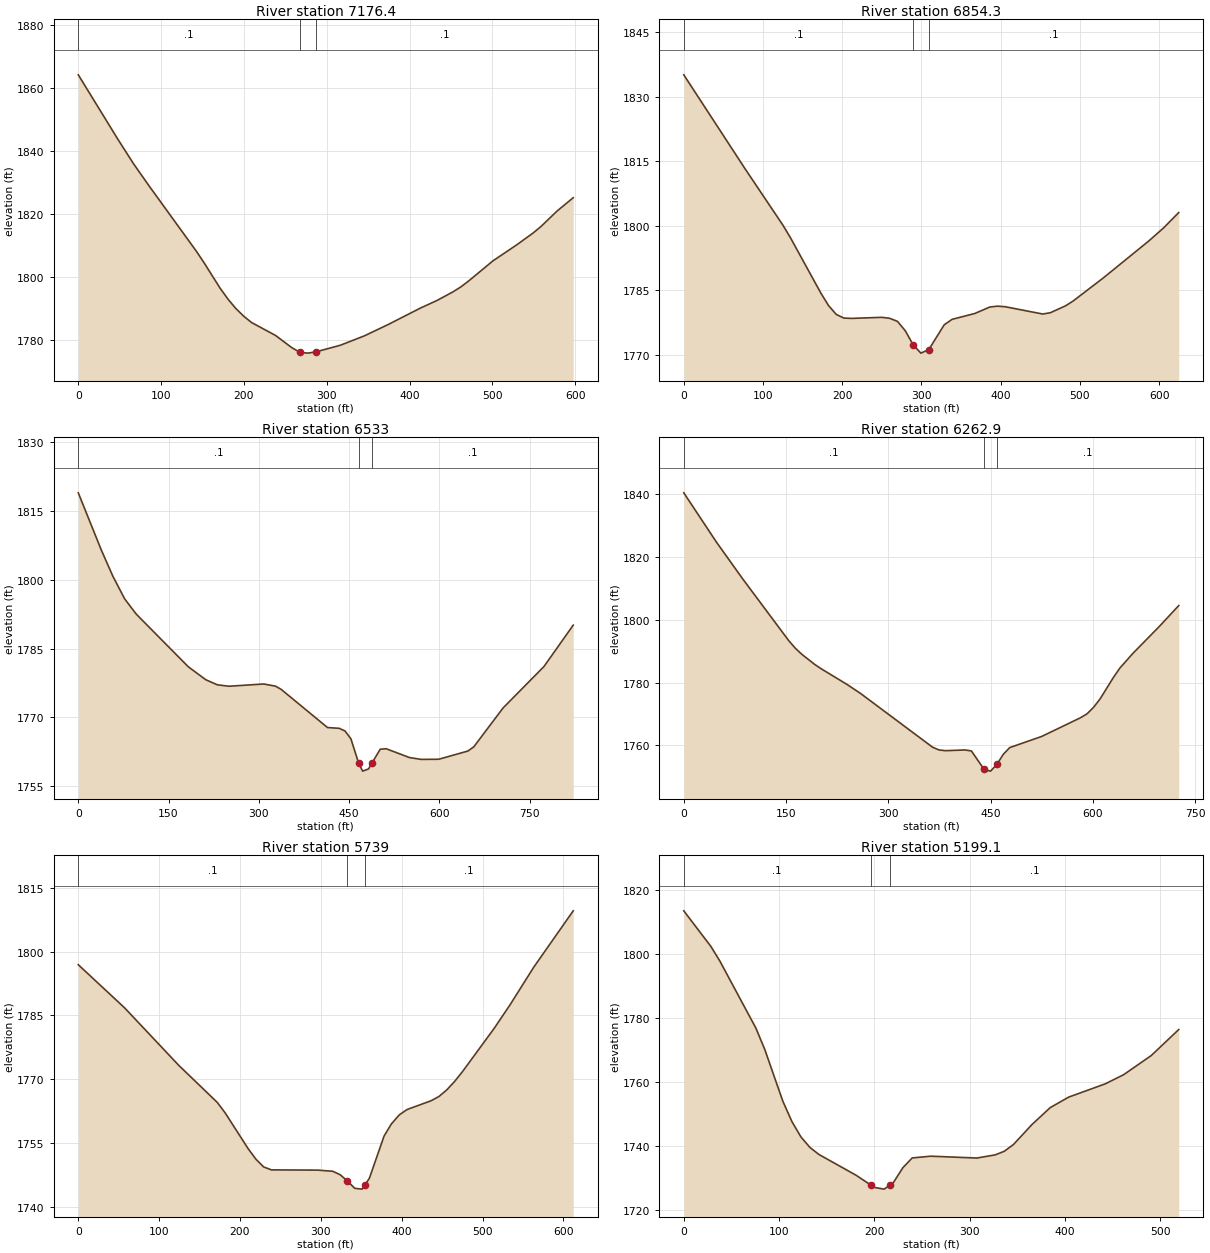
Type RM Length L Ch R = 1 ,7176.4  ,318.1,322.1,325.4
XS GIS Cut Line= 4
     1912527.462      371115.162     1912746.212      371109.953
     1912899.858      371083.912     1913105.587      370997.974
#Sta/Elev= 30
       0 1864.22    47.6 1843.87    66.6 1836.06    85.6 1828.95   142.7 1808.22
   152.2 1804.48   171.2 1796.56   180.8 1793.06   190.3 1790.09   199.8 1787.65
   209.3 1785.64   238.3 1781.54   257.8 1777.69   267.5 1776.22   277.2 1775.95
     287 1776.36   316.2 1778.43   345.4 1781.42   374.6 1785.08   413.4 1790.28
   432.8 1792.61   452.2 1795.35   461.9 1796.95   471.6 1798.89   500.7 1805.22
   529.8 1810.37   549.1 1814.04   558.8 1816.15   578.2 1821.04   597.6 1825.24
#Mann= 3 , 0 , 0
       0      .1       0   267.5    .045       0     287      .1       0
Bank Sta=267.5,287
XS Rating Curve= 0 ,0
Exp/Cntr=0.3,0.1

Type RM Length L Ch R = 1 ,6854.3  ,335.6,321.4,306.9
XS GIS Cut Line= 4
     1912608.192      371341.724     1912858.192      371349.537
     1912946.733      371349.537     1913222.775      371274.016
#Sta/Elev= 30
       0 1835.13      77 1813.37   125.1 1800.16   134.7 1797.21   173.2 1784.29
   182.8 1781.43   192.4 1779.39     202 1778.53   211.6 1778.45   250.1  1778.7
     260 1778.47   269.8 1777.75   279.6 1775.58   289.5 1772.31   299.3 1770.37
   309.2 1771.17   328.8 1776.97   338.7 1778.23   367.3 1779.59   386.4  1781.1
   395.9  1781.3   405.4 1781.18   453.1 1779.47   462.7 1779.77   481.8 1781.36
   491.3 1782.47   529.4 1787.84   586.7 1796.42   605.8 1799.53   624.8 1803.08
#Mann= 3 , 0 , 0
       0      .1       0   289.5    .045       0   309.2      .1       0
Bank Sta=289.5,309.2
XS Rating Curve= 0 ,0
Exp/Cntr=0.3,0.1

Type RM Length L Ch R = 1 ,6533    ,283.2,270,256.9
XS GIS Cut Line= 4
     1912561.317      371685.474     1912975.379      371675.057
     1913076.942      371599.537     1913298.296      371425.057
#Sta/Elev= 30
       0 1818.97    38.5 1806.41    57.8 1800.69    77.1 1795.83    96.3 1792.51
     183    1781   211.9 1778.19   231.2 1777.08   250.4 1776.77   308.2 1777.26
   327.5  1776.8   337.1  1776.1   414.2 1767.76   433.7 1767.59   443.4    1767
   453.1  1765.3   465.9 1760.03   472.6 1758.25   482.3 1758.72   488.7 1760.13
   501.8 1763.03   511.6 1763.14   550.5 1761.21   569.9 1760.81   599.1 1760.84
   647.7 1762.64   657.4 1763.56     706 1772.03     774 1781.08   822.6  1790.1
#Mann= 3 , 0 , 0
       0      .1       0   465.9    .045       0   488.7      .1       0
#XS Ineff= 2 , 0
                          503.18         1763.03
Permanent Ineff=
       F       F
Bank Sta=465.9,488.7
XS Rating Curve= 0 ,0
Exp/Cntr=0.3,0.1

Type RM Length L Ch R = 1 ,6262.9  ,506.7,523.9,541
XS GIS Cut Line= 4
     1913191.525      372122.974     1913272.254      371737.557
     1913324.337      371596.932     1913418.087      371440.682
#Sta/Elev= 30
       0 1840.32      48 1824.62    86.4 1812.96   153.7 1793.39   163.3 1790.97
   172.9 1789.02   192.1 1785.74   201.7 1784.35   240.1  1779.3   259.3 1776.52
     365 1759.42   374.6 1758.54   384.2 1758.32   412.5 1758.55   421.9 1758.24
   440.6 1752.35     450 1751.82   459.4    1754   468.8  1757.2   478.1  1759.3
     525 1762.85   582.1 1768.81   591.7 1770.08   601.3 1772.16   610.9 1774.86
     630 1781.54   639.6 1784.57   658.8 1789.27   697.2 1797.75     726 1804.46
#Mann= 3 , 0 , 0
       0      .1       0   440.6    .045       0   459.4      .1       0
Bank Sta=440.6,459.4
XS Rating Curve= 0 ,0
Exp/Cntr=0.3,0.1

Type RM Length L Ch R = 1 ,5739    ,555.2,539.9,523.4
XS GIS Cut Line= 4
     1913472.775       372120.37     1913720.171      371940.682
     1913793.087      371904.224     1913944.129      371737.557
#Sta/Elev= 30
       0 1796.89    57.3 1786.74   124.2 1773.23     172 1764.48   181.6 1762.05
   210.2 1753.58   219.8 1751.12   229.3 1749.31   238.9 1748.62   296.2 1748.56
   314.8 1748.29   323.9 1747.48   332.9 1746.01     342 1744.28   351.1 1744.09
   354.3 1744.98   360.1 1746.67   378.2 1756.56   387.3 1759.44   397.1 1761.57
   406.8 1762.83   436.2 1764.87     446 1765.87   455.7 1767.42   465.5 1769.43
   475.3 1771.76   514.4 1781.91     534 1787.44   563.3 1796.29   612.2 1809.57
#Mann= 3 , 0 , 0
       0      .1       0   332.9    .045       0   354.3      .1       0
Bank Sta=332.9,354.3
XS Rating Curve= 0 ,0
Exp/Cntr=0.3,0.1

Type RM Length L Ch R = 1 ,5199.1  ,314.5,308,300.8
XS GIS Cut Line= 4
     1913931.542      372396.412     1913981.021      372263.599
     1914030.501      372146.412     1914082.584       371901.62
#Sta/Elev= 30
       0 1813.54    28.4 1802.41    37.8 1797.85    75.6 1776.86      85 1770.13
   103.9 1753.97   113.4  1747.6   122.8 1742.82   132.3  1739.5   141.7  1737.3
   180.9 1730.76     196 1727.75   200.4 1726.94   210.2 1726.44  216.13 1727.67
     220 1728.55   229.8 1733.13   239.6  1736.2   259.2 1736.75   307.4 1736.17
   326.7 1737.16   336.3  1738.3   345.9 1740.42   365.2 1746.64   384.4 1751.95
   403.7 1755.23   442.2  1759.4   461.4 1762.25   490.3 1768.23   519.2 1776.38
#Mann= 3 , 0 , 0
       0      .1       0     196    .045       0  216.13      .1       0
Bank Sta=196,216.13
XS Rating Curve= 0 ,0
Exp/Cntr=0.3,0.1

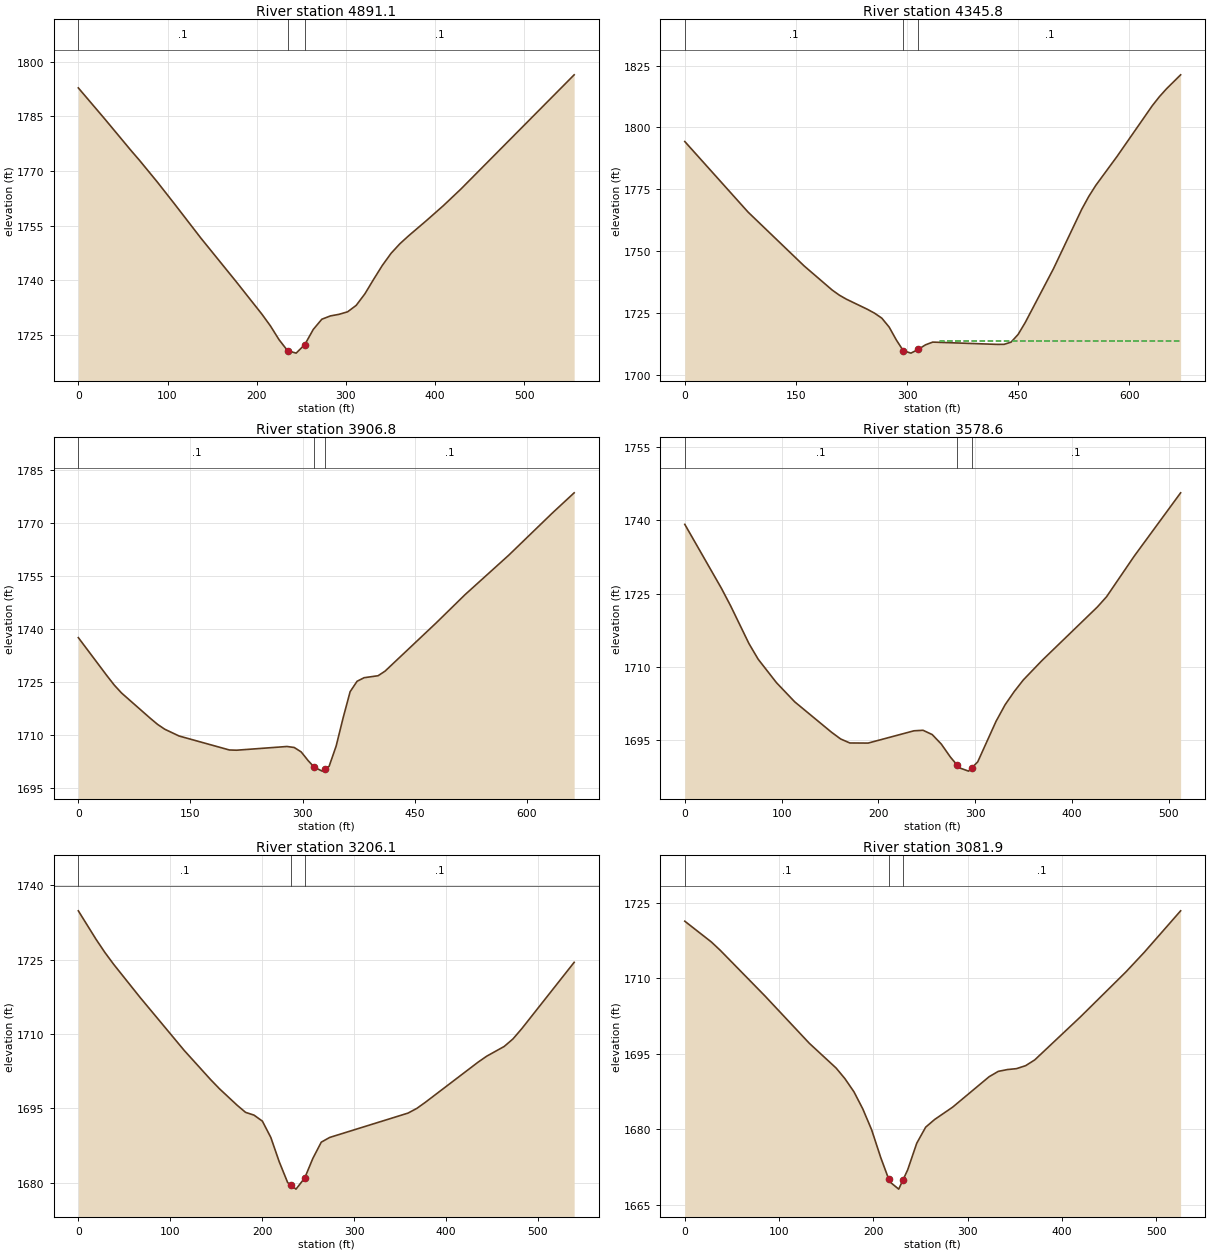
Type RM Length L Ch R = 1 ,4891.1  ,534.2,545.2,556
XS GIS Cut Line= 4
     1914235.796      372448.495     1914254.025      372253.182
     1914267.046      372138.599     1914326.942       371901.62
#Sta/Elev= 30
       0 1792.77    29.4 1784.32    58.8 1775.67    68.7 1772.86    88.3 1767.02
   107.9 1760.91   137.3 1751.58   176.6 1739.71   205.8 1730.68   215.4 1727.44
     225 1723.68   234.6 1720.65   244.2 1719.98   253.9 1722.32   263.4 1726.48
     273 1729.28   282.6 1730.19   292.3 1730.63   301.9 1731.32   311.5 1733.08
   321.3 1736.26     331  1740.2   340.8 1744.04   350.6 1747.36   360.4 1749.97
   370.2 1752.16   389.7 1756.23   409.2 1760.44   428.8 1764.98   555.9 1796.36
#Mann= 3 , 0 , 0
       0      .1       0   234.6    .045       0   253.9      .1       0
Bank Sta=234.6,253.9
XS Rating Curve= 0 ,0
Exp/Cntr=0.3,0.1

Type RM Length L Ch R = 1 ,4345.8  ,434.4,439,443.6
XS GIS Cut Line= 4
     1914553.504      372669.849     1914696.733      372469.328
     1914764.442      372372.974      1914894.65      372096.932
#Sta/Elev= 30
       0 1794.31    85.3 1765.87   161.1  1744.1     199 1734.36   208.5 1732.33
     218  1730.7   246.4 1726.61   256.2 1725.02     266 1723.02   275.9 1719.41
   285.7 1714.16     295 1709.87   305.3  1708.9   315.1 1710.39   324.9 1712.24
   334.7 1713.35   421.4 1712.43     431 1712.44   440.5 1713.34     450 1716.44
   459.6 1721.25   497.7 1742.95   535.9 1766.97   545.4 1772.15   554.9 1776.63
   583.6 1788.32   631.2  1808.8   640.8 1812.43   650.3 1815.59   669.4 1821.24
#Mann= 3 , 0 , 0
       0      .1       0     295    .045       0   315.1      .1       0
#XS Ineff= 2 , 0
                          345.21          1713.6
Permanent Ineff=
       F       F
Bank Sta=295,315.1
XS Rating Curve= 0 ,0
Exp/Cntr=0.3,0.1

Type RM Length L Ch R = 1 ,3906.8  ,311.2,328.1,344.6
XS GIS Cut Line= 4
     1914834.754      372742.766     1915095.171      372617.766
     1915183.712      372534.432     1915376.421       372370.37
#Sta/Elev= 30
       0 1737.63    38.5  1726.8    48.1  1724.2    57.8 1721.97    96.3 1714.81
   105.9 1713.11   115.6 1711.72   134.8  1709.8   202.2 1705.84   211.8 1705.78
   279.2 1706.83   288.9 1706.55   298.2  1705.3   307.6 1702.82   315.7 1700.97
   326.3 1699.86   330.7 1700.51   335.6 1701.23     345 1706.95   354.3  1714.9
   363.7 1722.33     373 1725.28   382.4 1726.29   401.1 1726.85   410.4 1728.14
   478.6 1741.74   517.5 1749.79   575.9 1760.94   634.3 1772.88   663.5  1778.6
#Mann= 3 , 0 , 0
       0      .1       0   315.7    .045       0   330.7      .1       0
Bank Sta=315.7,330.7
XS Rating Curve= 0 ,0
Exp/Cntr=0.3,0.1

Type RM Length L Ch R = 1 ,3578.6  ,369.8,372.5,375.1
XS GIS Cut Line= 4
     1914884.667      372899.016      1915111.23      372917.245
     1915233.626      372914.641     1915384.667      372854.745
#Sta/Elev= 30
       0 1739.21    37.9  1726.1    47.4 1722.51    66.3  1714.8    75.8 1711.61
    94.7 1706.81   113.6 1702.88   151.5 1696.68     161 1695.29   170.5 1694.47
   189.4 1694.45   236.7 1696.96   246.1 1697.07   255.6 1696.19     265 1694.24
   274.4 1691.58   281.5 1689.91   283.8 1689.37   293.2 1688.71   296.5 1689.38
   302.6 1690.61   321.5 1698.89   330.9  1702.3   340.3 1704.99   349.7 1707.37
   368.8 1711.31   426.2  1722.3   435.7  1724.4   464.4 1732.74   512.2 1745.66
#Mann= 3 , 0 , 0
       0      .1       0   281.5    .045       0   296.5      .1       0
Bank Sta=281.5,296.5
XS Rating Curve= 0 ,0
Exp/Cntr=0.3,0.1

Type RM Length L Ch R = 1 ,3206.1  ,132,124.3,116.5
XS GIS Cut Line= 4
     1914790.483      373227.141     1914962.358       373245.37
     1915071.733      373255.787     1915324.337      373208.912
#Sta/Elev= 30
       0 1734.84    19.2 1729.12    28.8 1726.47    38.4 1724.06    67.2 1717.37
   115.2 1706.68     144 1700.78   153.6 1698.94   172.8 1695.62     182 1694.18
   191.2 1693.62   200.3 1692.41   209.5 1689.11   218.6 1684.23   227.8 1680.02
   231.4 1679.49   236.9 1678.69   246.4 1680.95   255.2 1684.88   264.4 1688.17
   273.6 1689.12   358.8 1694.03   368.4 1694.98   377.9 1696.24     435  1704.3
   444.5 1705.52   463.5 1707.48     473 1708.99   482.5 1711.04   539.6 1724.45
#Mann= 3 , 0 , 0
       0      .1       0   231.4    .045       0   246.4      .1       0
Bank Sta=231.4,246.4
XS Rating Curve= 0 ,0
Exp/Cntr=0.3,0.1

Type RM Length L Ch R = 1 ,3081.9  ,90.2,88.5,86.8
XS GIS Cut Line= 4
     1914837.141      373344.328     1915032.454      373378.182
     1915115.787      373357.349     1915339.745      373266.203
#Sta/Elev= 30
       0 1721.32    28.3 1717.18    37.8 1715.51      85 1706.49   132.2 1697.07
   160.5 1692.18   169.9 1690.06   179.4 1687.47   188.8 1684.07   198.2 1679.91
   207.8 1674.43   216.3 1670.13   217.3 1669.62   226.9 1668.15   231.3 1669.92
   236.4 1671.98     246 1677.25   255.5 1680.45     265 1681.97   284.1 1684.42
   322.8 1690.46   332.5 1691.52   342.2 1691.88   351.8 1692.06   361.5 1692.65
   371.2  1693.8   419.5 1702.31   467.9 1711.26   487.2 1715.12   525.9 1723.38
#Mann= 3 , 0 , 0
       0      .1       0   216.3    .045       0   231.3      .1       0
Bank Sta=216.3,231.3
XS Rating Curve= 0 ,0
Exp/Cntr=0.3,0.1

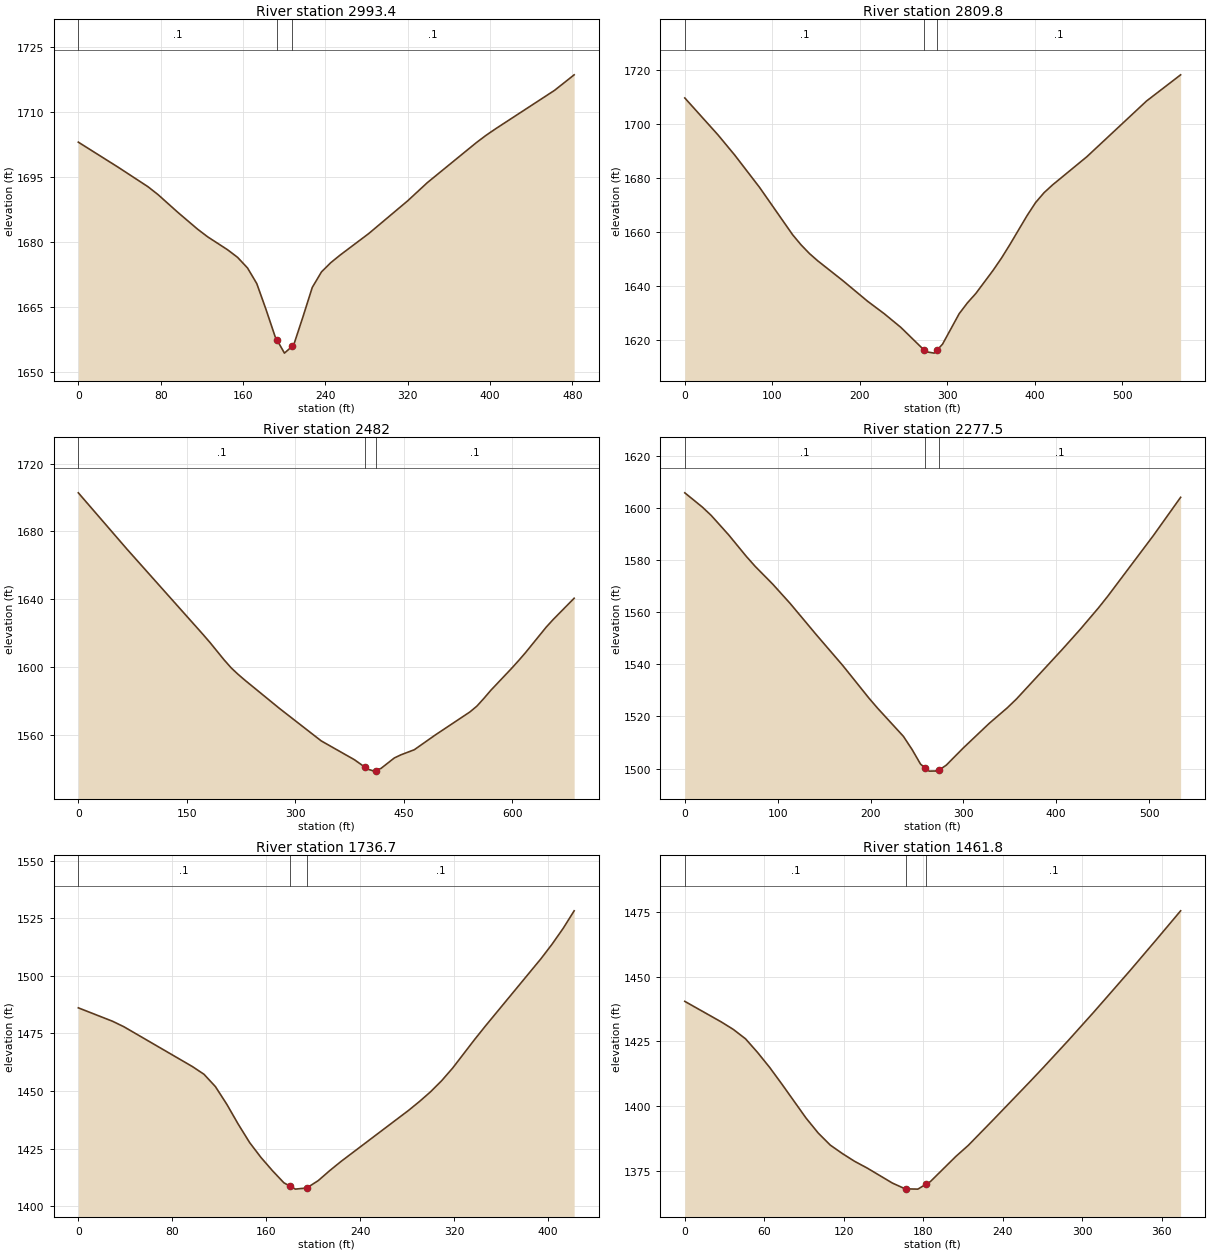
Type RM Length L Ch R = 1 ,2993.4  ,184.9,183.6,182.2
XS GIS Cut Line= 4
     1914895.084      373453.703     1915059.146       373464.12
     1915152.896       373432.87     1915356.021      373352.141
#Sta/Elev= 30
       0 1703.08    38.7 1697.29    67.7 1692.78    77.4 1690.97    96.7 1686.86
     116 1682.95   125.7  1681.2     145 1678.22   154.7 1676.47   164.4 1674.01
   173.4  1670.4   182.4  1664.4   191.3  1658.1   192.8 1657.47   200.3 1654.33
   207.8 1655.91   209.3 1656.23   218.3 1662.74   227.3  1669.5   236.3 1673.11
   245.2 1675.21   254.2 1676.95   282.2 1681.96   320.2 1689.56   339.2 1693.74
   386.8 1702.98   396.3 1704.68   405.8 1706.22   462.8 1715.06   481.8 1718.64
#Mann= 3 , 0 , 0
       0      .1       0   192.8    .045       0   207.8      .1       0
Bank Sta=192.8,207.8
XS Rating Curve= 0 ,0
Exp/Cntr=0.3,0.1

Type RM Length L Ch R = 1 ,2809.8  ,327.2,327.8,328.2
XS GIS Cut Line= 4
       1914925.9      373612.557     1915134.233      373628.182
     1915248.817      373581.307     1915441.525      373448.495
#Sta/Elev= 30
       0 1709.48      38  1695.8      57 1688.38    85.5 1676.38   123.4 1658.82
     133 1655.11   142.4 1651.95   151.9 1649.25   180.4 1641.97   208.9 1634.29
     228 1629.66     247  1624.6   273.5 1616.23   275.6 1615.61   285.1 1615.08
   288.5 1616.26   294.6 1618.38   313.7 1629.69   323.2 1633.72   332.7 1637.15
   352.2 1645.61     362 1650.23   371.7 1655.28   391.2 1665.92     401 1670.78
   410.7 1674.44   420.5 1677.34   459.5 1687.71   527.8 1708.34   566.8 1718.04
#Mann= 3 , 0 , 0
       0      .1       0   273.5    .045       0   288.5      .1       0
Bank Sta=273.5,288.5
XS Rating Curve= 0 ,0
Exp/Cntr=0.3,0.1

Type RM Length L Ch R = 1 ,2482    ,224.7,204.5,184.9
XS GIS Cut Line= 4
     1914985.796      373896.412     1915321.733      373896.412
     1915441.525      373849.537     1915592.567      373688.078
#Sta/Elev= 30
       0 1702.77    67.2 1669.58   172.8 1619.04   182.4 1614.29   201.6 1604.21
   211.2 1599.58   220.8 1595.72   230.4 1592.21   278.4 1575.48   335.9 1556.41
   381.9 1545.28   396.4 1540.87   400.3  1539.7   409.4 1538.57   411.4 1538.92
   418.6 1540.18     437 1546.34   446.2  1548.2   464.6 1551.18   493.4 1559.82
   541.5 1573.48   551.1 1576.89   560.7 1581.39   570.3 1586.18   599.2  1599.2
   608.8 1603.74   618.4 1608.47   647.2  1623.6   656.8 1628.07   685.7 1640.58
#Mann= 3 , 0 , 0
       0      .1       0   396.4    .045       0   411.4      .1       0
Bank Sta=396.4,411.4
XS Rating Curve= 0 ,0
Exp/Cntr=0.3,0.1

Type RM Length L Ch R = 1 ,2277.5  ,546.4,540.8,534.5
XS GIS Cut Line= 4
     1915451.942       374245.37     1915517.046       374057.87
     1915558.712      373935.474      1915644.65      373747.974
#Sta/Elev= 30
       0 1605.72    18.9 1600.25    28.4 1597.07    47.3 1589.57    66.2 1581.37
    75.6 1577.59    94.5 1570.78   113.4 1563.33   141.8 1551.24   170.1 1539.52
   198.5 1526.92   207.7 1523.11   235.4 1512.35   244.7 1507.34   253.9 1501.68
   258.4 1500.37   263.1    1499   272.4 1499.06   273.4  1499.3   281.6 1501.29
   300.1 1507.94   327.8 1517.29   347.4  1523.3   357.2 1526.66   406.4 1545.62
     426 1553.42   445.6 1561.63   455.5 1566.06   504.6 1589.31     534    1604
#Mann= 3 , 0 , 0
       0      .1       0   258.4    .045       0   273.4      .1       0
Bank Sta=258.4,273.4
XS Rating Curve= 0 ,0
Exp/Cntr=0.3,0.1

Type RM Length L Ch R = 1 ,1736.7  ,271,274.9,278.8
XS GIS Cut Line= 4
     1916076.942      374201.099     1916074.337      374055.266
      1916082.15      373948.495     1916084.754      373779.224
#Sta/Elev= 30
       0 1486.11    29.2 1480.27    38.9 1477.87    97.2 1460.58     107 1457.25
   116.7 1451.91   126.4 1444.24   136.1 1435.62   145.9 1427.56   155.6 1421.06
   165.3 1415.36     175 1410.12     180 1408.71   184.8 1407.35   194.5 1407.86
     195 1408.02   204.2 1411.01     214 1415.36   223.7 1419.38   281.1 1441.52
   290.5 1445.42   299.9 1449.63   309.3 1454.41   318.8 1459.98   337.6 1472.46
     347 1478.44     394 1507.49   403.4 1513.77   412.8 1520.61   422.2 1528.26
#Mann= 3 , 0 , 0
       0      .1       0     180    .045       0     195      .1       0
Bank Sta=180,195
XS Rating Curve= 0 ,0
Exp/Cntr=0.3,0.1

Type RM Length L Ch R = 1 ,1461.8  ,164.3,162.8,161.4
XS GIS Cut Line= 4
     1916262.271      374149.016     1916340.396      374047.453
      1916361.23       373964.12     1916340.396      373805.266
#Sta/Elev= 30
       0 1440.52    27.5 1432.57    36.6 1429.67    45.8 1426.04    54.9 1420.76
    64.1 1414.92    73.2 1408.55    91.5 1395.36   100.7 1389.55   109.8 1384.89
     119 1381.59   128.1 1378.63   137.7 1375.99   156.8 1370.16   166.3 1367.97
     167 1367.96   175.9 1367.85     182 1369.74   185.4  1370.8   204.5 1380.47
     214 1384.81   232.9 1394.74   261.2 1409.82   270.6 1414.93   289.4 1425.36
   308.3 1436.16   317.7 1441.66   336.6 1452.77   355.4  1464.1   374.2 1475.56
#Mann= 3 , 0 , 0
       0      .1       0     167    .045       0     182      .1       0
Bank Sta=167,182
XS Rating Curve= 0 ,0
Exp/Cntr=0.3,0.1

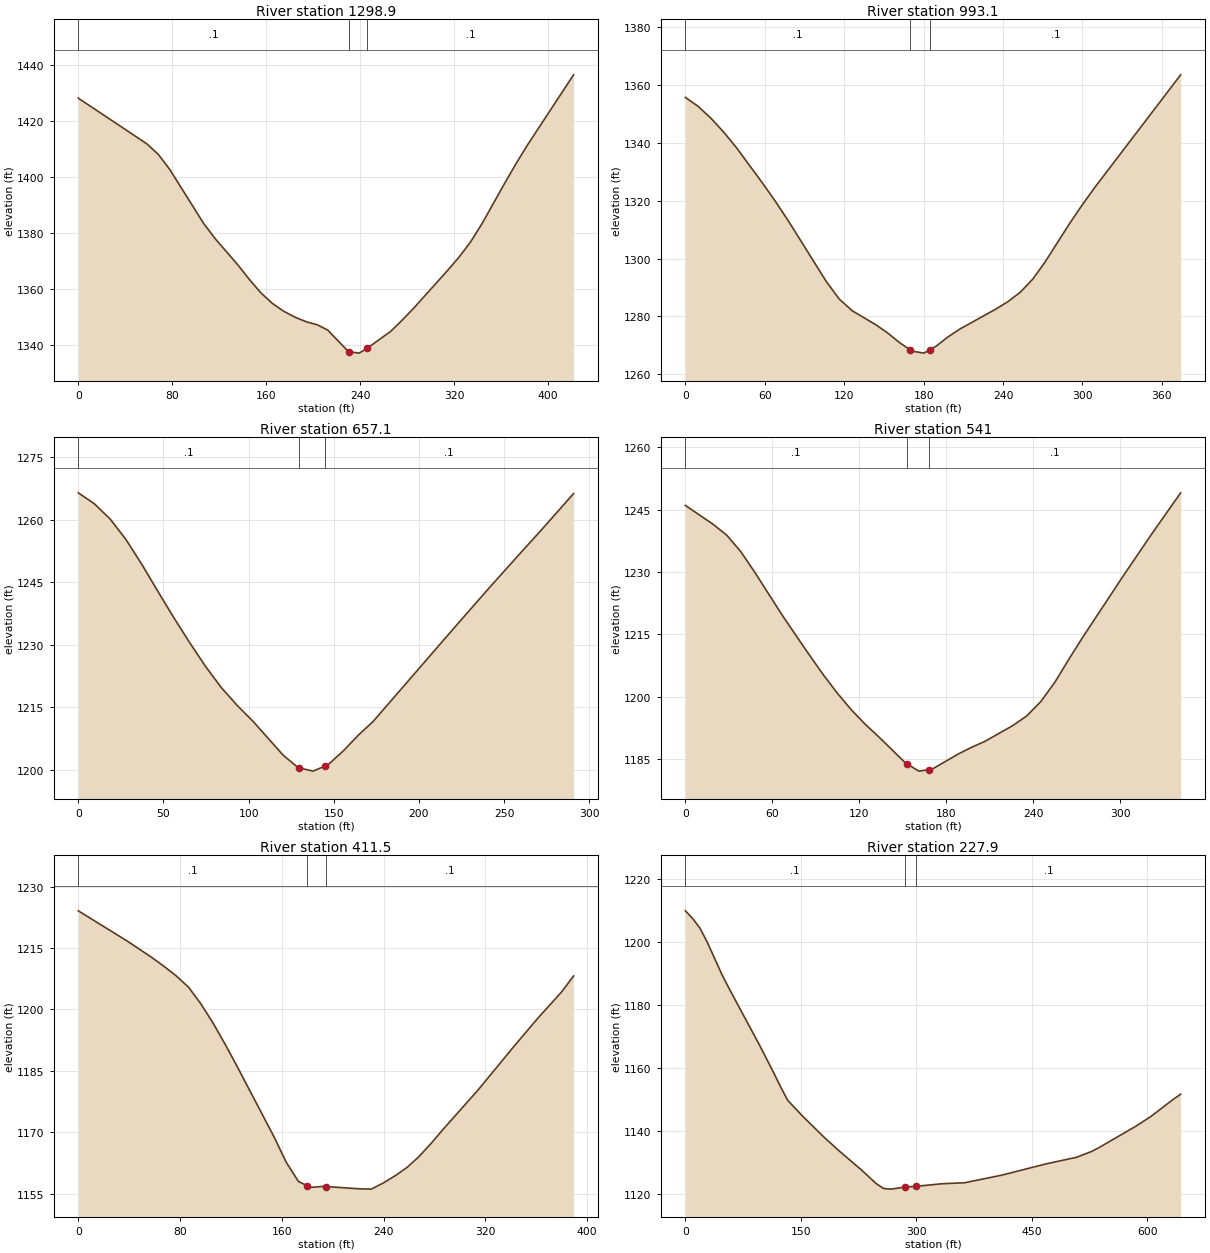
Type RM Length L Ch R = 1 ,1298.9  ,303.4,305.8,308.2
XS GIS Cut Line= 4
     1916420.474      374224.537     1916506.412      374050.057
     1916519.433      373979.745     1916464.745      373833.912
#Sta/Elev= 30
       0 1428.24    58.4 1411.93    68.1 1408.18    77.8 1402.85     107 1383.36
   116.7 1378.02   136.2 1368.57   145.9 1363.41   155.6  1358.7   165.3 1354.97
     175 1352.15   184.8 1350.01   194.5 1348.36   203.4 1347.36   212.4 1345.46
   230.2 1337.73   230.9 1337.69   239.2 1337.22   245.9 1338.92     266 1344.97
   275.7 1348.93   285.5  1353.2   314.7 1366.82   324.4 1371.56   334.1 1376.93
   343.9 1383.48   363.4 1398.05   373.1 1405.07   382.8 1411.68   421.8 1436.57
#Mann= 3 , 0 , 0
       0      .1       0   230.9    .045       0   245.9      .1       0
Bank Sta=230.9,245.9
XS Rating Curve= 0 ,0
Exp/Cntr=0.3,0.1

Type RM Length L Ch R = 1 ,993.1   ,341.7,336.1,330.2
XS GIS Cut Line= 4
     1916748.817      374219.328       1916800.9      374104.745
      1916832.15      374000.578     1916811.317      373862.557
#Sta/Elev= 30
       0 1355.72     9.7  1352.6    19.4 1348.46      29 1343.69    38.7 1338.28
    58.1  1326.2    67.8 1319.93    77.5 1313.24   106.5 1292.05   116.2 1286.04
   125.9 1282.02     144 1277.11     153 1274.23   162.1 1270.87   169.8 1268.48
   171.2 1268.04   180.2 1267.33   184.8 1268.52   189.3 1269.68   198.4 1272.93
   207.4 1275.66   234.6 1282.56   243.9 1285.18   253.2 1288.44   262.5 1292.92
   271.8 1298.85   290.4  1312.2   299.8 1318.53   309.1 1324.45   374.2 1363.51
#Mann= 3 , 0 , 0
       0      .1       0   169.8    .045       0   184.8      .1       0
Bank Sta=169.8,184.8
XS Rating Curve= 0 ,0
Exp/Cntr=0.3,0.1

Type RM Length L Ch R = 1 ,657.1   ,117,116.1,115.2
XS GIS Cut Line= 4
     1917093.001      374193.287     1917145.084      374104.745
     1917147.688      374034.432     1917098.209      373927.662
#Sta/Elev= 26
       0 1266.42     9.3 1263.84    18.7 1260.13      28  1255.2    37.4 1249.18
    46.7 1242.78      56 1236.51    65.4 1230.45    74.7 1224.76      84 1219.65
    93.4 1215.34   102.7 1211.52   120.3 1203.43   129.1 1200.44   129.7 1200.38
   137.9 1199.61   144.7 1200.81   146.7 1201.16   155.5 1204.42   164.3 1208.19
   173.1 1211.53   222.1 1234.66   241.7  1243.8   261.3 1252.74   271.2 1257.18
   290.8 1266.24
#Mann= 3 , 0 , 0
       0      .1       0   129.7    .045       0   144.7      .1       0
Bank Sta=129.7,144.7
XS Rating Curve= 0 ,0
Exp/Cntr=0.3,0.1

Type RM Length L Ch R = 1 ,541     ,128.8,129.5,130.3
XS GIS Cut Line= 4
     1917188.704      374195.891      1917261.62      374083.912
      1917261.62      374010.995     1917186.099      373899.016
#Sta/Elev= 30
       0    1246    19.1 1241.47    28.6 1238.82    38.2  1234.9    47.7 1230.02
    66.8  1219.6    76.4 1214.67    85.9 1209.84    95.4 1205.14     105 1200.77
   114.5 1196.83   124.1 1193.35   133.6 1190.27   151.9 1184.04   152.7 1183.87
     161  1182.1   167.7 1182.44   170.1 1182.56   188.3 1186.23   197.4 1187.83
   206.5 1189.24   225.8 1193.05   235.5 1195.39   245.1 1198.81   254.8 1203.45
   264.4 1208.95   274.1 1214.32     303 1229.57   322.3 1239.46   341.6 1249.03
#Mann= 3 , 0 , 0
       0      .1       0   152.7    .045       0   167.7      .1       0
Bank Sta=152.7,167.7
XS Rating Curve= 0 ,0
Exp/Cntr=0.3,0.1

Type RM Length L Ch R = 1 ,411.5   ,180.6,183.6,186.4
XS GIS Cut Line= 4
     1917326.942      374227.141     1917389.442      374096.932
     1917392.046      374010.995     1917308.712      373875.578
#Sta/Elev= 30
       0 1224.07    38.5 1216.69    57.8 1212.69    67.4 1210.52      77  1208.2
    86.7 1205.42    96.3 1201.41   105.9 1196.71   115.6 1191.44   125.2 1185.91
     154 1168.86   163.5 1162.71   173.1 1158.03   180.1 1156.96   182.6 1156.58
   192.2 1156.82   195.1 1156.78   220.9 1156.24   230.4 1156.16   239.8 1157.66
   249.1 1159.42   258.5 1161.46   267.8 1164.08   277.2 1167.25   286.5 1170.63
   314.6 1180.46   342.6 1191.02   361.4  1197.9   380.1 1204.32   389.4 1208.17
#Mann= 3 , 0 , 0
       0      .1       0   180.1    .045       0   195.1      .1       0
Bank Sta=180.1,195.1
XS Rating Curve= 0 ,0
Exp/Cntr=0.3,0.1

Type RM Length L Ch R = 1 ,227.9   ,231.5,227.9,224.4
XS GIS Cut Line= 4
     1917444.129      374292.245     1917545.692      374206.307
      1917582.15      373979.745     1917449.337      373732.349
#Sta/Elev= 30
       0 1209.88     9.5 1207.43      19 1204.37    28.5 1199.87    47.5 1189.62
      57 1185.09      95 1167.81     114 1158.78   123.5 1154.04     133 1149.63
   152.2 1144.66   180.8 1137.79     200 1133.54   228.7 1127.54   247.8 1123.22
   257.3 1121.67   266.9 1121.45   284.8 1122.08   299.8 1122.35   333.8 1123.17
   362.5 1123.47   410.9 1125.89     469  1129.5   507.8 1131.55   527.1 1133.36
   536.8 1134.58   585.2 1141.45   604.6 1144.53   633.6 1149.97   643.3 1151.61
#Mann= 3 , 0 , 0
       0      .1       0   284.8    .045       0   299.8      .1       0
Bank Sta=284.8,299.8
XS Rating Curve= 0 ,0
Exp/Cntr=0.3,0.1

Chan Stop Cuts=-1
Use User Specified Reach Order=0
Composite Channel Slope=5